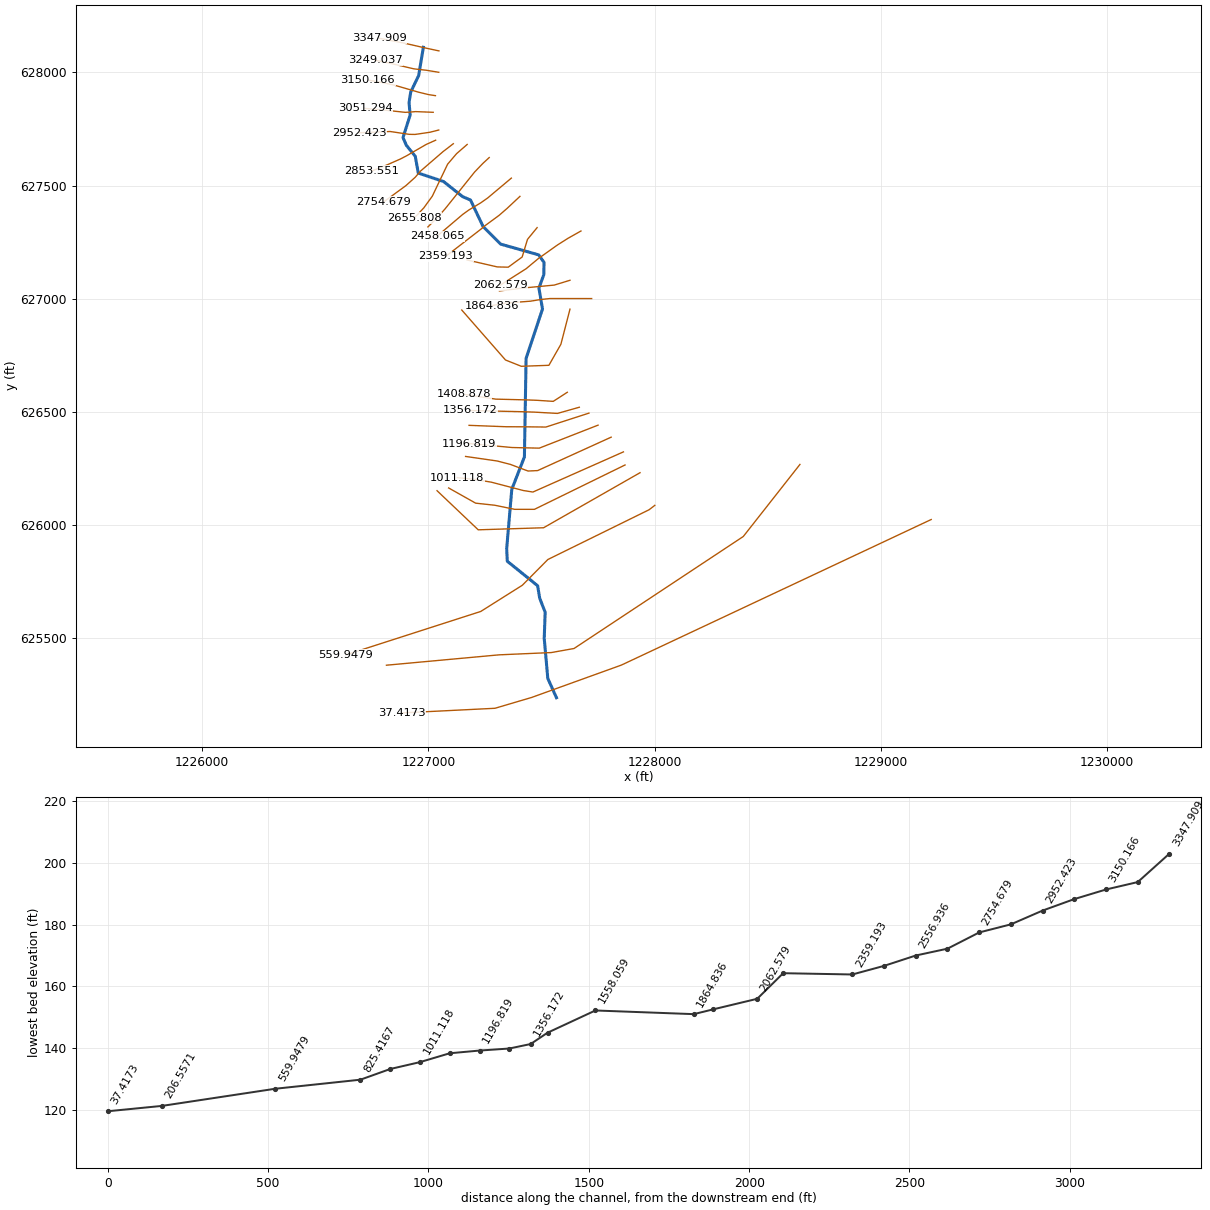
--- 266_ras.prj (project) ---

Proj Title=266
Current Plan=p01
Default Exp/Contr=0.3,0.1
English Units
Geom File=g01
Flow File=f01
Plan File=p01
Y Axis Title=Elevation
X Axis Title(PF)=Main Channel Distance
X Axis Title(XS)=Station
BEGIN DESCRIPTION:
RFD model 266 exported to HEC-RAS
END DESCRIPTION:

--- 266_ras.p01 (plan) ---

Plan Title=Plan 01
Program Version=4.10
Short Identifier=Plan 01
Geom File=g01
Flow File=f01
Subcritical Flow
Calc Critical at every XS
Secant Critical Depth

--- 266_ras.f01 (steady flow) ---

Flow Title=Flow 01
Program Version=5.01
Number of Profiles= 5
Profile Names=10yr,25yr,50yr,100yr,500yr
River Rch & RM=266,27,3347.909
  363.21  429.79  511.44  541.07  627.85
River Rch & RM=266,27,2853.551
  367.97  436.25  519.36  550.51  640.39
River Rch & RM=266,27,2655.808
  370.78  440.08  524.05   556.1  647.83
River Rch & RM=266,27,2556.936
  373.56  443.86  528.69  561.65  655.22
River Rch & RM=266,27,2458.065
  379.93  452.55  539.33  574.39  672.24
River Rch & RM=266,27,2359.193
  382.61  456.21  543.82  579.78  679.44
River Rch & RM=266,27,2143.589
  390.49  466.98  557.04  595.66  700.76
River Rch & RM=266,27,1924.623
  397.28  476.31   568.5  609.47  719.36
River Rch & RM=266,27,1864.836
  400.62   480.9  574.13  616.26  728.53
River Rch & RM=266,27,1558.059
  410.37  494.34  590.65  636.26  755.61
River Rch & RM=266,27,1408.878
  429.63  521.02  623.47  676.18  810.04
River Rch & RM=266,27, 1289.67
  436.24  530.22  634.81  690.04  829.04
River Rch & RM=266,27,1103.968
     442  538.25   644.7  702.15  845.69
River Rch & RM=266,27,1011.118
  444.13  541.22  648.36  706.64  851.87
River Rch & RM=266,27,918.2673
  447.64  546.13  654.41  714.07  862.12
Boundary for River Rch & Prof#=266,27,1
Up Type= 0
Dn Type= 2
Boundary for River Rch & Prof#=266,27,2
Up Type= 0
Dn Type= 2
Boundary for River Rch & Prof#=266,27,2
Up Type= 0
Dn Type= 2
Boundary for River Rch & Prof#=266,27,2
Up Type= 0
Dn Type= 2
Boundary for River Rch & Prof#=266,27,2
Up Type= 0
Dn Type= 2

--- 266_ras.g01 (geometry) ---

Geom Title=266
Program Version=4.10

River Reach=266,27
Reach XY= 30
 1226978.1679693628111.3238619271226957.33463848627986.323899618
 1226922.3346467627913.8239221561226914.83464755627867.157269564
1226919.83464448627812.1572857431226888.16798426627712.157316342
1226903.16797884627677.9906593871226942.33463255627629.657339254
 1226955.6679598627555.4906942311227067.33459243627517.990702119
1227151.50123232627451.3240527941227186.50122157627436.324056223
1227242.33453502 627318.824089511227319.83450989627241.324110269
1227488.16779219627193.8241194781227511.50111767 627160.49079536
1227510.66778301627106.3241447841227489.00112102627047.157496334
1227504.83444698626954.6575233181227432.26698431626736.179577336
 1227424.8344516626300.4910531681227369.00113058626157.157763982
1227346.50112961625895.4911756631227349.08292469625839.617212182
1227483.24954862625731.2839070911227492.41621099625676.283923149
 1227516.5828687625613.7839410191227512.41619993625498.783975279
1227528.24952343625321.2840275011227566.58284299625236.284051596

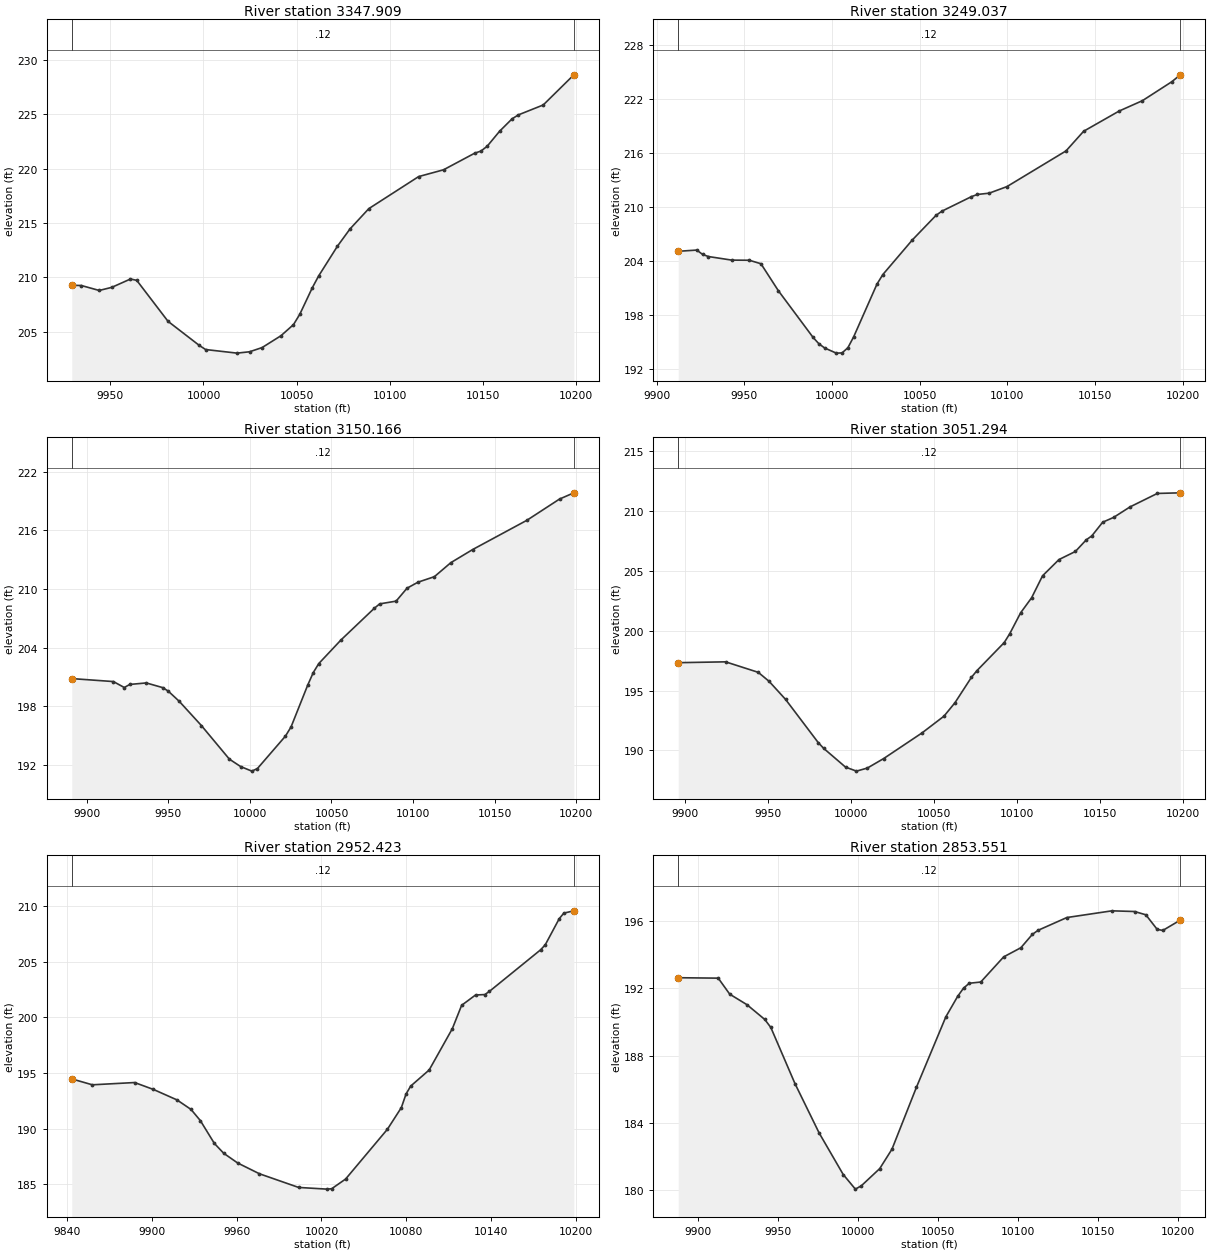
Type RM Length L Ch R = 1 ,3347.909,98.871500,98.871500,98.871500
XS GIS Cut Line= 6
1227047.01127421628095.6589113911227042.67252237628096.334655328
1226978.88825778 628110.106822691226976.95093006628110.603573447
1226892.30241036628130.1016686371226783.51913623628151.086683069
#Sta/Elev= 30
9929.355209.26839934.479209.24889944.066208.79359950.779209.07719960.849209.8473
9964.205209.72359980.987205.95359997.769203.735210001.14203.358210017.98203.0282
10024.71203.153210031.45203.539710041.55204.627610048.28205.652210051.65206.5997
10058.38209.046810061.75210.123310071.85212.866510078.58214.450510088.67216.3199
 10115.4219.269610128.77219.894810145.48 221.42310148.82221.615310152.16  222.06
10158.84223.443710165.52224.582510168.87224.943610182.23225.858210198.65228.6309
#Mann= 3 , 0 , 0
9929.355    0.12       09929.355    0.12       010198.65    0.12       0
#XS Ineff= 2 , 0
       0                               0
Bank Sta=9929.355,10198.65
Exp/Cntr=0.3,0.1

Type RM Length L Ch R = 1 ,3249.037,98.871500,98.871500,98.871500
XS GIS Cut Line= 6
1227046.31447033628000.8935830591226990.84313823628009.957086648
1226958.59380973628013.4755396791226935.88958923628016.213095096
1226827.64259074628041.4875424481226765.33065491628054.286975382
#Sta/Elev= 30
9912.352205.09529922.939205.23179926.264204.74529929.588204.51249942.886204.1161
9952.859204.10139959.507203.71539969.474200.70959989.279195.5248 9992.58194.8241
9995.881194.355410002.48193.789610005.78193.813110009.09194.389710012.39195.6008
10025.65201.442510029.01202.511110045.86206.360410059.34209.084510062.71209.5526
10079.55 211.16510082.92 211.40510089.66211.548910099.77212.276810133.46216.2393
10143.51218.4222 10163.8 220.67110177.01221.815310193.75223.915610198.64224.6879
#Mann= 3 , 0 , 0
9912.352    0.12       09912.352    0.12       010198.64    0.12       0
#XS Ineff= 2 , 0
       0                               0
Bank Sta=9912.352,10198.64
Exp/Cntr=0.3,0.1

Type RM Length L Ch R = 1 ,3150.166,98.871500,98.871500,98.871500
XS GIS Cut Line= 6
 1227031.5796645627897.6117738321227002.60003124627901.956823085
 1226958.3819202627912.5633499441226849.50684078627944.163558529
 1226793.0390805627956.3272968011226731.93650513627966.719665251
#Sta/Elev= 30
9890.737200.84069916.262200.53699922.945199.92949926.319200.24269936.441200.3966
9946.562199.91549949.936 199.5559956.684198.51279970.256196.03659987.403192.6063
9994.262191.855710001.15191.383510004.59191.646410021.78194.962210025.22195.9017
10035.44200.174710038.84 201.45410042.23202.376810055.81204.783510076.18208.0112
10079.57208.475610089.64208.755210096.35210.078610103.06210.691710113.13211.2551
 10123.2212.686110136.62214.0308 10169.9217.022410189.87 219.18810198.65219.8244
#Mann= 3 , 0 , 0
9890.737    0.12       09890.737    0.12       010198.65    0.12       0
#XS Ineff= 2 , 0
       0                               0
Bank Sta=9890.737,10198.65
Exp/Cntr=0.3,0.1

Type RM Length L Ch R = 1 ,3051.294,98.871500,98.871500,98.871500
XS GIS Cut Line= 6
1227021.71199334627824.0468189571226943.99112362627827.114054281
1226916.94716577627824.9190074871226898.10047572627823.860457509
 1226787.2267647627835.8384393381226720.20892639627841.040550505
#Sta/Elev= 30
9896.081197.33459924.601197.40529944.301196.52789950.868195.77129960.718194.2729
9980.432190.65929983.723190.17599996.884188.610410003.48188.275110010.05188.5322
10019.88189.326310043.01191.470410056.21192.867210062.81193.985710072.71196.1025
10076.01196.662510092.51199.014510095.81199.7496 10102.4201.5026   10109202.7546
 10115.6204.5921 10125.5 205.94910135.39206.625410141.97207.600910145.26207.9237
10151.85209.069410158.43209.4711 10168.3210.346910184.75211.472910198.61211.5241
#Mann= 3 , 0 , 0
9896.081    0.12       09896.081    0.12       010198.61    0.12       0
#XS Ineff= 2 , 0
       0                               0
Bank Sta=9896.081,10198.61
Exp/Cntr=0.3,0.1

Type RM Length L Ch R = 1 ,2952.423,98.871600,98.871600,98.871600
XS GIS Cut Line= 6
1227046.24219904627745.7358401361227007.35434075627735.879546792
1226941.52075508627726.1842657491226915.39858676627726.642370889
1226831.21946275627739.2165904481226694.15579325627733.421350225
#Sta/Elev= 30
9843.318194.46939857.875 193.9379887.799194.14149901.126193.51869917.785192.5772
9927.709191.72069934.312190.71589944.215188.66279950.813 187.7779960.657186.9036
9976.139185.927510003.84184.698710023.91 184.54610027.22184.5792 10037.1185.4531
10066.71189.939810076.55191.885110079.84193.098710083.12 193.81710096.24195.2719
10112.65198.995310119.21201.093910129.06202.021710135.64202.061310138.93202.3546
 10175.1206.089510178.39206.541410188.25208.886310191.54 209.39310198.62209.5992
#Mann= 3 , 0 , 0
9843.318    0.12       09843.318    0.12       010198.62    0.12       0
#XS Ineff= 2 , 0
       0                               0
Bank Sta=9843.318,10198.62
Exp/Cntr=0.3,0.1

Type RM Length L Ch R = 1 ,2853.551,98.871500,98.871500,98.871500
XS GIS Cut Line= 6
1227032.45040287627700.6536109481226989.83807496627681.546461415
1226903.63028276627631.5579839381226875.86625738627617.230198996
1226815.97686152627590.8231123461226750.09491077627564.448514305
#Sta/Elev= 30
 9887.51 192.6169912.532192.58999919.723191.6392 9930.51191.01519941.653190.1384
9945.429189.66379960.535186.3329 9975.64183.40689990.691180.94429998.299180.0766
10002.03180.275110013.53181.2938 10021.2182.448110036.44186.1058 10054.9190.2984
10062.28191.510710065.95191.997710069.54192.287910076.71192.359710091.05193.8511
10101.81194.394210108.98195.185310112.56195.427210130.57196.185310158.76 196.583
 10172.9196.542610179.97196.347810187.04 195.48610190.57 195.41910201.53196.0332
#Mann= 3 , 0 , 0
 9887.51    0.12       0 9887.51    0.12       010201.53    0.12       0
#XS Ineff= 2 , 0
       0                               0
Bank Sta=9887.51,10201.53
Exp/Cntr=0.3,0.1

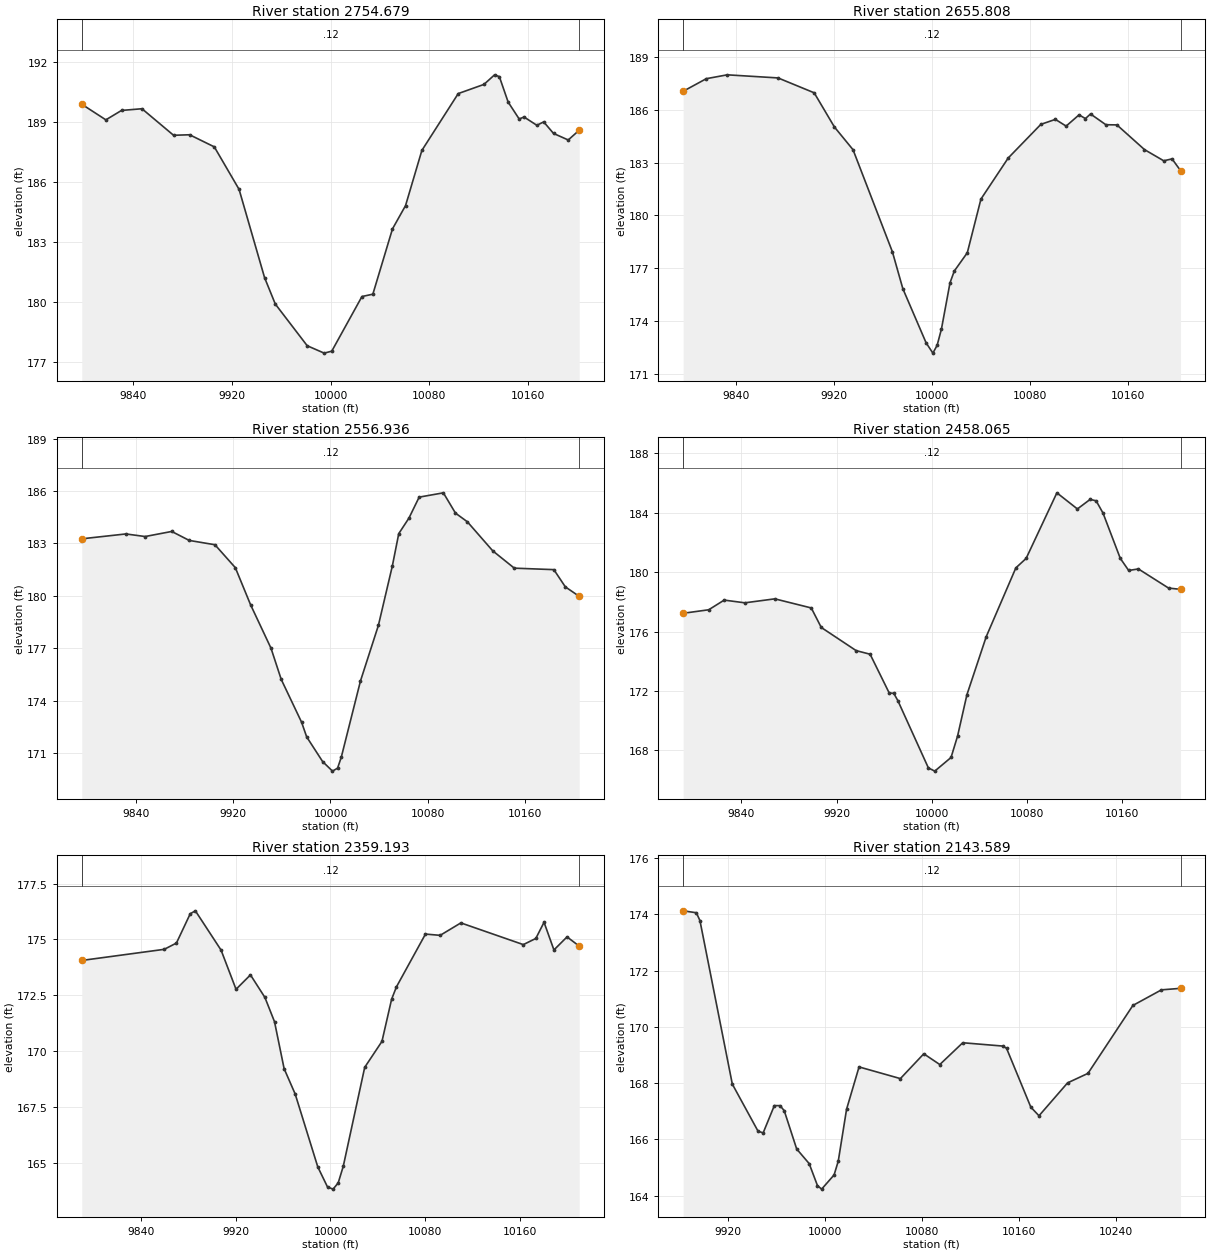
Type RM Length L Ch R = 1 ,2754.679,98.871500,98.871500,98.871500
XS GIS Cut Line= 6
1227110.57239233627685.1591057121227064.89242214627649.981891378
1226965.68761287627564.2293744971226942.07856699627536.805343889
1226900.65640401627499.5623956831226802.15363333627427.515151558
#Sta/Elev= 30
9798.517 189.8859818.016189.10569830.695189.57559847.259189.66079872.857188.3345
9885.867188.35999905.861187.75499925.929185.6303 9946.58181.21819955.253179.9001
9981.115177.81469994.841 177.445   10001177.542610025.46180.274210034.29180.3915
10050.18183.653610060.76 184.818   10074187.577910103.45190.418510124.27190.8766
 10132.9191.355910136.77191.263410143.89189.992210152.81189.149310156.78 189.247
10167.14188.833310172.68189.003610180.63188.426910192.56188.098910201.44188.5886
#Mann= 3 , 0 , 0
9798.517    0.12       09798.517    0.12       010201.44    0.12       0
#XS Ineff= 2 , 0
       0                               0
Bank Sta=9798.517,10201.44
Exp/Cntr=0.3,0.1

Type RM Length L Ch R = 1 ,2655.808,98.871500,98.871500,98.871500
XS GIS Cut Line= 6
1227171.93042621627681.9829175841227124.87311878627641.125327671
1227085.43311166627594.7774883461227017.66947435627453.175534229
1226979.82490181627401.1134966251226937.85445108627356.537255264
#Sta/Elev= 30
9796.842187.05369815.778187.76999832.882 187.9899874.372187.81299903.891186.9681
9920.407185.02779935.628183.73579967.788177.93779976.313175.8445 9995.31172.7701
10000.86 172.18310004.35172.630110007.85173.550510014.84176.173110018.33 176.843
10028.98177.884210040.12180.932610062.39183.264810089.07185.176310100.94185.4587
10109.71185.076810120.25 185.71510125.47 185.50510129.64185.765910142.17 185.155
10151.18185.145310173.71183.742910189.42183.107210196.24183.214810203.17 182.549
#Mann= 3 , 0 , 0
9796.842    0.12       09796.842    0.12       010203.17    0.12       0
#XS Ineff= 2 , 0
       0                               0
Bank Sta=9796.842,10203.17
Exp/Cntr=0.3,0.1

Type RM Length L Ch R = 1 ,2556.936,98.871500,98.871500,98.871500
XS GIS Cut Line= 6
1227269.27647102627623.9249051661227240.76305136627597.687683491
1227204.57075548627559.8522457821227073.66517172627396.532415333
1227037.36656686627356.2109352671226998.23076137627317.339480939
#Sta/Elev= 30
9795.089183.26029831.398183.53889847.298183.39119869.211183.68199883.619183.1677
9904.809182.92079921.605 181.6089934.202179.47969950.999176.99769959.397175.2174
9976.194172.76249980.393171.92259993.542170.509510001.66169.963310005.86170.1338
10008.95170.772210024.71175.121910039.46178.299410050.98181.707910056.26183.5572
10064.66184.447110073.07185.645810093.01185.892310102.99184.731310112.79184.2344
10133.72182.570410151.47181.580510184.06181.495810193.51180.509910204.94179.9678
#Mann= 3 , 0 , 0
9795.089    0.12       09795.089    0.12       010204.94    0.12       0
#XS Ineff= 2 , 0
       0                               0
Bank Sta=9795.089,10204.94
Exp/Cntr=0.3,0.1

Type RM Length L Ch R = 1 ,2458.065,98.871500,98.871500,98.871500
XS GIS Cut Line= 6
1227367.12450865627533.1581107881227262.04854435627444.960343129
1227231.49615176 627423.593696151227179.61869694627392.470692862
1227151.92271367627372.4717019841227038.76398356627276.323807081
#Sta/Elev= 30
9791.175177.23469812.667 177.4729825.645178.12349843.002  177.94 9868.17178.2076
9898.766177.59469907.157176.28039936.473 174.7199948.161174.47799964.176171.8706
9968.063171.83919971.439171.35529997.079166.820710002.44166.602510016.12167.5215
10021.62168.970710029.46171.753410045.65175.656310070.54180.294310079.16180.9303
10104.99185.349310122.21184.262710132.88184.905210137.94184.812510143.73183.9825
10158.21180.936110165.26180.118810173.41180.223310198.74178.934210208.81178.8465
#Mann= 3 , 0 , 0
9791.175    0.12       09791.175    0.12       010208.81    0.12       0
#XS Ineff= 2 , 0
       0                               0
Bank Sta=9791.175,10208.81
Exp/Cntr=0.3,0.1

Type RM Length L Ch R = 1 ,2359.193,215.604800,215.604800,215.604800
XS GIS Cut Line= 6
1227405.02192467627452.369017736 1227348.0389134627398.988268667
1227312.51566025627368.1293340631227248.19360511627320.927651576
1227237.03569967627310.8600918051227078.15702073 627187.86389928
#Sta/Elev= 30
 9789.56174.05419859.327174.55189869.648174.83279881.334176.1463 9885.68176.2766
9907.409174.51789920.081172.76269932.289173.40749944.497172.39889952.636171.3098
9960.775169.20599970.125168.07169989.261164.80559997.507163.904810002.19 163.811
10006.54164.091610010.82164.834710028.96169.266310043.55170.427810051.73172.3173
10055.82172.871110080.37175.234910092.82175.178710110.33175.735710163.17174.7635
10173.74175.038210180.71175.763910189.08174.523910200.16175.109110210.46174.6966
#Mann= 3 , 0 , 0
 9789.56    0.12       0 9789.56    0.12       010210.46    0.12       0
#XS Ineff= 2 , 0
       0                               0
Bank Sta=9789.56,10210.46
Exp/Cntr=0.3,0.1

Type RM Length L Ch R = 1 ,2143.589,81.009700,81.009700,81.009700
XS GIS Cut Line= 6
 1227480.9930276627314.240674809 1227438.4589332627262.254559457
1227414.82888082627184.2753864381227353.39074451627139.378286824
1227304.94913697627140.5597894341227171.43934071627171.278857589
#Sta/Elev= 30
9883.254174.12699894.148174.05899897.114173.78029923.822167.96319945.017166.2895
9949.256166.22869958.464167.19869963.192 167.197 9966.62 167.0199976.904165.6554
9987.189165.13649994.045164.35269997.473164.227710007.76164.733610011.19165.2241
10018.04167.069810028.33168.574410062.41168.159110081.71 169.04110094.92168.6592
10113.85169.434510146.66169.317410149.95 169.23910169.98167.144410176.71166.8367
10200.28 168.00710217.11168.345210254.14170.760910277.71171.315910293.45171.3697
#Mann= 3 , 0 , 0
9883.254    0.12       09883.254    0.12       010293.45    0.12       0
#XS Ineff= 2 , 0
       0                10023.86       0
Bank Sta=9883.254,10293.45
Exp/Cntr=0.3,0.1

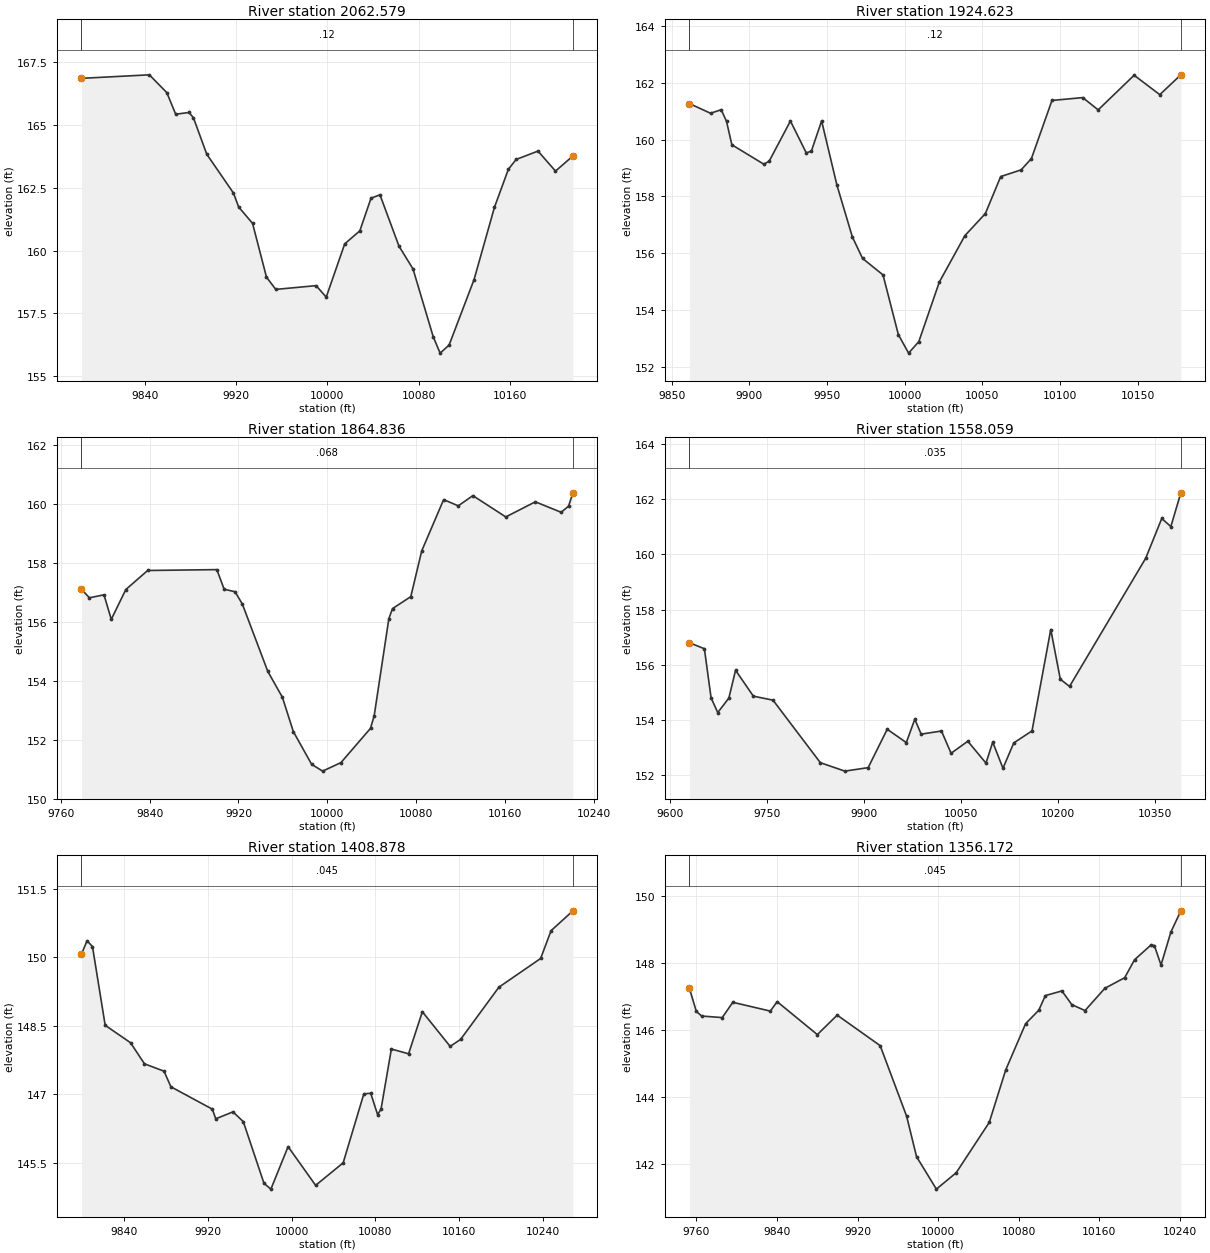
Type RM Length L Ch R = 1 ,2062.579,137.955700,137.955700,137.955700
XS GIS Cut Line= 6
1227674.89966403627299.3902575751227617.49626485627267.035038521
1227570.99473506627237.5453194451227486.17338284627177.255129695
1227432.28526063627132.4791636791227318.08955236 627059.95142254
#Sta/Elev= 30
9784.746166.86719844.168167.00689859.504 166.2989867.273165.43689878.928165.5077
9882.813165.29639894.468 163.846 9917.89162.29639922.404161.74279934.599161.0897
9946.795158.94799954.926 158.4599990.291158.60859999.144158.151110015.34 160.273
10028.57160.791210038.38162.092410046.21162.227410062.86160.182610075.15159.2747
10092.88156.571110098.92  155.9210106.78156.241710128.65158.850810146.53161.7328
10158.71163.243710165.45163.634110184.64163.969110199.98 163.17210215.25163.7738
#Mann= 3 , 0 , 0
9784.746    0.12       09784.746    0.12       010215.25    0.12       0
#XS Ineff= 2 , 0
       0                10049.98       0
Bank Sta=9784.746,10215.25
Exp/Cntr=0.3,0.1

Type RM Length L Ch R = 1 ,1924.623,59.787400,59.787400,59.787400
XS GIS Cut Line= 4
1227626.31785005627081.4846583461227556.60919538627060.217611149
1227418.37338865627047.2210823151227314.40115795627034.224553496
#Sta/Elev= 30
9861.394161.27099875.012160.92869881.873161.05519885.303 160.6439888.733159.8192
9909.314159.13489912.744159.23839926.464160.65629936.657159.53279939.952159.5953
9946.543  160.669956.429158.39159966.315156.57599972.905 155.8159986.087155.2337
9995.973153.129310002.56 152.47810009.15152.884510022.33154.979110038.81 156.617
10051.99157.393810061.88158.698910075.07158.935510081.68159.3348 10094.9161.3804
10114.74161.481210124.66161.047810147.81162.268610164.34161.5846 10177.9162.2832
#Mann= 3 , 0 , 0
9861.394    0.12       09861.394    0.12       0 10177.9    0.12       0
#XS Ineff= 2 , 0
       0                               0
Bank Sta=9861.394,10177.9
Exp/Cntr=0.3,0.1

Type RM Length L Ch R = 1 ,1864.836,306.776900,306.776900,306.776900
XS GIS Cut Line= 6
 1227722.1535283627000.6706439931227538.16577502627000.800401273
1227495.82838768626996.3166704161227451.51063084626989.094058832
1227346.97685732626981.0148713081227281.32467939626969.958832763
#Sta/Elev= 30
9778.549157.11549785.704156.82729798.828156.92879805.389156.09529818.513 157.108
9838.198157.75419900.534157.78369907.095 157.1189916.938 157.0329923.499156.6166
9946.465154.32739959.589153.45199969.472152.28569985.975151.17439995.876150.9439
10012.42151.234210039.01152.396210042.33152.823910055.57156.123210058.86156.4608
10075.32156.866610085.19158.421110104.93160.1601 10118.1159.948210131.26160.2953
10160.94159.571810187.56160.084810210.85159.7289 10217.5159.938110221.44  160.39
#Mann= 3 , 0 , 0
9778.549   0.068       09778.549   0.068       010221.44   0.068       0
#XS Ineff= 2 , 0
       0                               0
Bank Sta=9778.549,10221.44
Exp/Cntr=0.3,0.1

Type RM Length L Ch R = 1 ,1558.059,149.181200,149.181200,149.181200
XS GIS Cut Line= 6
1227626.31785005626953.8823752111227586.18618891626798.832877323
1227533.13485003626705.6893052611227411.23826224626701.234612703
1227341.17809719626729.177684322  1227147.831168626950.075311199
#Sta/Elev= 30
9629.579156.79449652.789156.57599663.131154.79589673.473 154.2599690.709154.7862
9701.051155.7953 9728.63154.85459759.024154.70979832.357152.43999870.239152.1333
9906.382152.25979935.924153.65359965.475 153.1699978.608154.01739988.459153.4759
10019.93153.589510034.81152.7815 10060.7153.218410088.86152.424610099.33 153.186
10115.15152.2371 10131.9153.157110160.13 153.59410189.19157.274110203.94155.4701
10218.24155.207810336.21159.861110361.07161.303510375.16161.011710390.62162.2354
#Mann= 3 , 0 , 0
9629.579   0.035       09629.579   0.035       010390.62   0.035       0
#XS Ineff= 2 , 0
       0                               0
Bank Sta=9629.579,10390.62
Exp/Cntr=0.3,0.1

Type RM Length L Ch R = 1 ,1408.878,52.705300,52.705300,52.705300
XS GIS Cut Line= 6
1227614.50282386626586.4350599051227552.29816225626546.252575755
 1227481.4034422626550.867844924  1227436.859999626552.639790818
1227297.89987051626556.1258447321227159.62431452626576.983038932
#Sta/Elev= 30
9799.766 150.0679805.113150.35949810.253150.22939822.346148.50679846.532148.1244
9859.795147.66289878.453147.50089885.028 147.1599924.482146.66979927.769146.4578
9944.208146.61029954.059146.3943 9973.76145.04469980.327144.91779996.741145.8484
   10023144.999910049.25145.494310068.94147.004410075.51147.016910082.07146.5497
10085.35146.6703 10095.2147.986110111.61147.882110124.73148.802710151.24148.0447
10161.19148.197210197.69149.3404 10237.5149.969810247.46150.579210268.29151.0136
#Mann= 3 , 0 , 0
9799.766   0.045       09799.766   0.045       010268.29   0.045       0
#XS Ineff= 2 , 0
       0 9933.12                       0
Bank Sta=9799.766,10268.29
Exp/Cntr=0.3,0.1

Type RM Length L Ch R = 1 ,1356.172,66.502800,66.502800,66.502800
XS GIS Cut Line= 6
1227667.67044184626520.2709130941227570.84562123626492.956426486
1227468.34864697626498.702761441 1227423.7970593626500.268975928
1227421.79811606626500.3339821991227183.49546969 626505.92843309
#Sta/Elev= 30
9752.957147.24149759.816146.55099765.142146.41069785.595146.36519796.068146.8214
 9833.32146.55889840.138146.83999880.053145.85699899.769146.43849942.487145.5268
9968.763143.41889978.612142.21179998.309141.2434   10018141.732610050.82143.2347
10067.23144.805210086.92146.181310100.04146.585510106.61147.021610123.02147.1612
10132.86146.750910145.99146.574710165.68 147.23910185.37147.555510195.21 148.093
10211.62148.5345 10214.9148.513410221.47147.934110231.31148.921610241.17149.5521
#Mann= 3 , 0 , 0
9752.957   0.045       09752.957   0.045       010241.17   0.045       0
#XS Ineff= 2 , 0
       09924.649                       0
Bank Sta=9752.957,10241.17
Exp/Cntr=0.3,0.1

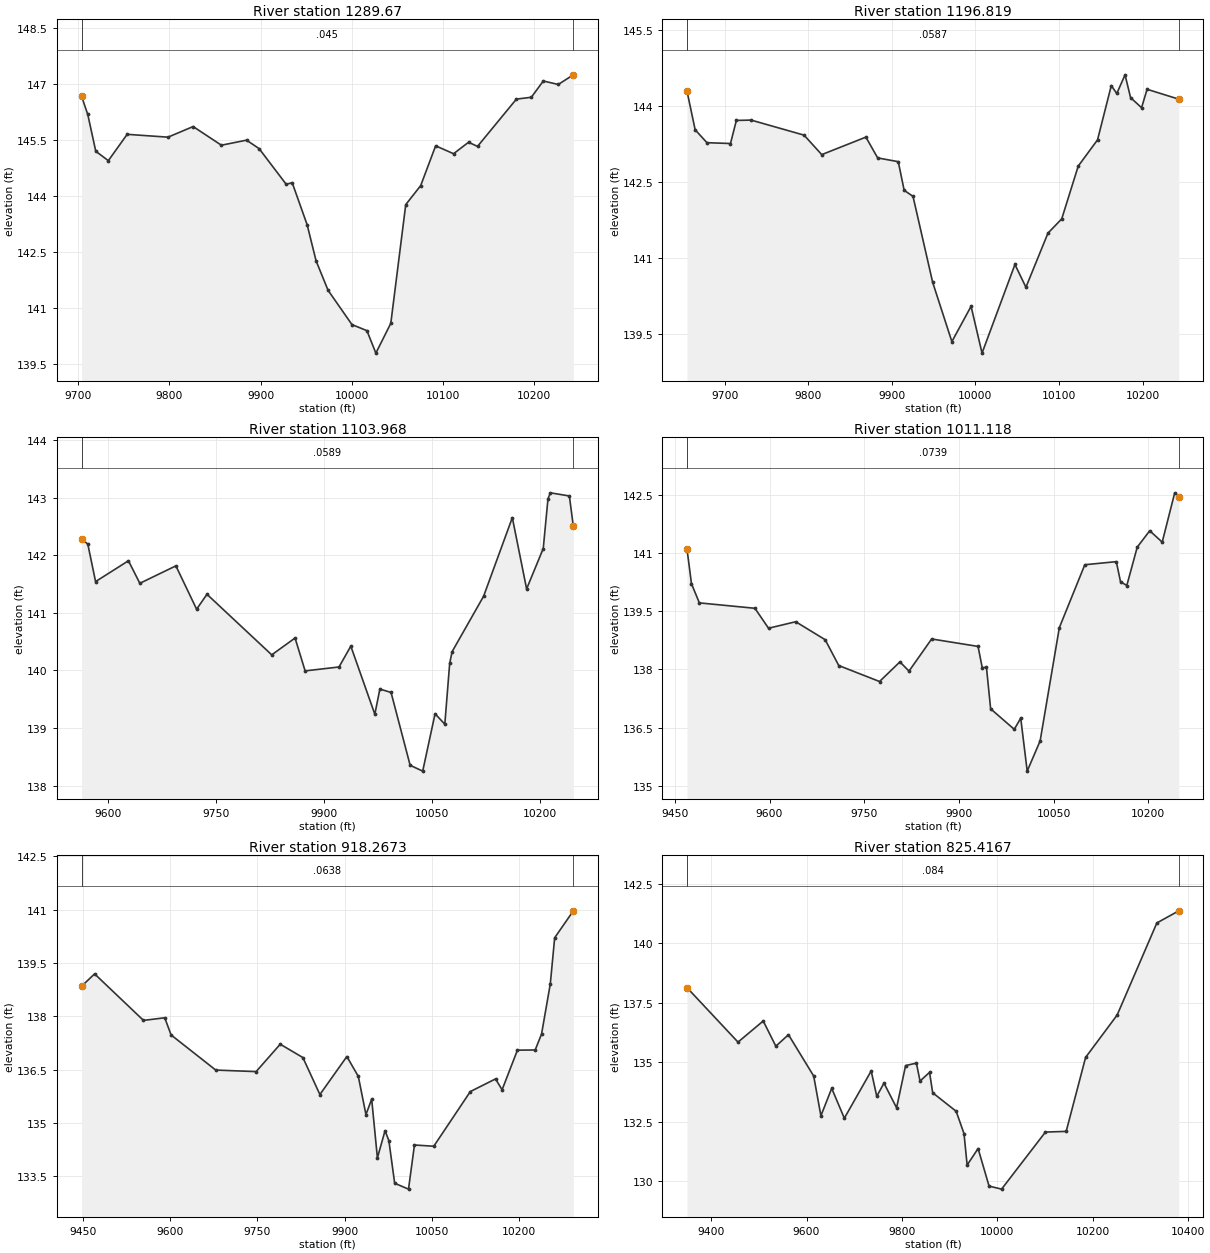
Type RM Length L Ch R = 1 , 1289.67,92.850600,92.850600,92.850600
XS GIS Cut Line= 6
1227710.20453617626494.2778553961227519.95180565626432.731549218
1227424.40640837626433.7733975651227422.40652317626433.751969069
1227343.43643248626434.1038301441227180.06128561626440.231082156
#Sta/Elev= 30
9703.489146.66719710.363146.1777 9719.14145.19359732.933144.94189753.623145.6459
 9798.45145.57019826.036145.8541 9857.07145.35479884.656145.49019898.449145.2646
 9928.22144.30939934.782144.35289951.187143.22879961.031142.26119974.155141.4752
 10000.4140.556610016.81140.394810026.65139.793410043.05140.590310059.46143.7658
10075.86144.274110092.28145.338910111.97145.127310128.39145.433810138.24145.3231
10180.92146.587410197.34146.637410210.47147.072710226.88146.979510243.46147.2376
#Mann= 3 , 0 , 0
9703.489   0.045       09703.489   0.045       010243.46   0.045       0
#XS Ineff= 2 , 0
       09915.404                       0
Bank Sta=9703.489,10243.46
Exp/Cntr=0.3,0.1

Type RM Length L Ch R = 1 ,1196.819,92.850600,92.850600,92.850600
XS GIS Cut Line= 6
1227750.37562531626441.1102374351227490.53233728626339.470448345
1227425.40123147626340.928152099 1227423.4013463626340.906723604
1227369.49469376626342.2554452721227181.79299274626359.776235402
#Sta/Elev= 30
9654.838144.29129664.643143.52739678.734 143.2739706.918143.25659713.963143.7112
9731.578 143.718 9794.99143.42159816.127143.03799868.971143.38269883.062 142.973
9907.723142.89889914.768 142.3359925.337142.21659948.892140.52229971.863139.3553
9994.835140.050610007.96139.128710047.34140.874210060.49140.425910086.85141.4915
10103.33141.7726 10123.1142.812610146.17143.328310162.64144.397310169.23144.2416
10179.12144.609310185.71144.160810198.89143.961210205.48144.324810243.44144.1298
#Mann= 3 , 0 , 0
9654.838  0.0587       09654.838  0.0587       010243.44  0.0587       0
#XS Ineff= 2 , 0
       09909.419                       0
Bank Sta=9654.838,10243.44
Exp/Cntr=0.3,0.1

Type RM Length L Ch R = 1 ,1103.968,92.850600,92.850600,92.850600
XS GIS Cut Line= 6
1227808.26925379626387.9426194581227483.35603282626240.254791752
1227440.92409279626238.260484412 1227362.8773467626267.612664201
1227304.27903662626282.7153195381227164.86844166626302.752373267
#Sta/Elev= 30
9562.786142.28739571.541142.19729582.352141.54549628.069141.90729643.926141.5153
9694.072141.81889722.903141.06519737.318141.32469827.415140.2718 9859.85140.5643
9873.852139.99289920.989140.06089937.411140.42279970.813139.23939977.835139.6773
9993.399139.617910019.94138.351810037.42138.250310054.61139.247810068.17139.0661
10074.94140.123410078.33140.3276 10122.1141.289810162.08142.656610181.96141.4183
10205.09142.120110211.69142.9851   10215143.088410241.42143.033810246.97142.5048
#Mann= 3 , 0 , 0
9562.786  0.0589       09562.786  0.0589       010246.97  0.0589       0
#XS Ineff= 2 , 0
       0 9919.69                       0
Bank Sta=9562.786,10246.97
Exp/Cntr=0.3,0.1

Type RM Length L Ch R = 1 ,1011.118,92.850500,92.850500,92.850500
XS GIS Cut Line= 6
1227862.61837438626322.9599752721227462.37359866626145.400770396
1227419.98831114626152.1423758791227278.21480392626189.115071753
1227205.48748104626201.1540129011227127.84313971626209.203690083
#Sta/Elev= 30
9469.197141.10349476.357140.20379488.834139.71069576.854139.57149598.389139.0574
9641.459139.22499688.118138.76219709.654138.09649774.259 137.6859806.562138.1908
9820.918137.9523 9856.81 138.7819930.313138.58919936.957138.04029943.602138.0521
9950.252136.98129987.695 136.4539997.906136.741210008.17 135.37610028.67136.1556
10059.09139.073310099.43140.693310149.31140.773110155.96140.257210165.94140.1584
10182.47141.146510202.26 141.56910222.05141.276110241.84142.546110248.32142.4469
#Mann= 3 , 0 , 0
9469.197  0.0739       09469.197  0.0739       010248.32  0.0739       0
#XS Ineff= 2 , 0
       09901.384                       0
Bank Sta=9469.197,10248.32
Exp/Cntr=0.3,0.1

Type RM Length L Ch R = 1 ,918.2673,92.850600,92.850600,92.850600
XS GIS Cut Line= 6
1227869.70739013626265.066346794 1227469.1780014626068.936911628
 1227382.2464996626068.9344743641227294.26568574626086.997731686
1227209.32348239626096.2356053291227089.91565982626163.457121342
#Sta/Elev= 30
9447.577138.84669470.064139.19649554.084137.88749590.615 137.9619601.574137.4776
9678.288  136.499747.696136.44679789.112 137.2189828.064136.84169857.288135.8021
9903.634 136.8719923.319136.31169936.442135.23779946.285135.67139956.127134.0187
 9969.25134.78449975.812 134.5069985.814133.305710009.59133.1406 10019.8134.3819
10053.02134.347510115.83135.885310159.14136.241210170.44135.936110196.79137.0507
10227.28 137.05510238.21 137.50110253.27138.9123 10260.8140.212610292.89  140.97
#Mann= 3 , 0 , 0
9447.577  0.0638       09447.577  0.0638       010292.89  0.0638       0
#XS Ineff= 2 , 0
       09879.041                       0
Bank Sta=9447.577,10292.89
Exp/Cntr=0.3,0.1

Type RM Length L Ch R = 1 ,825.4167,265.468800,265.468800,265.468800
XS GIS Cut Line= 4
1227935.87153694626230.8027707931227509.63352636  625987.5445088
1227220.64673695 625978.442562671227038.60781452626151.379538998
#Sta/Elev= 30
9349.353138.13389456.343135.84629509.228136.73349535.671135.67519562.114136.1576
9614.999134.42289630.109132.75429652.774 133.9079679.217 132.653 9735.49 134.636
9747.213133.57249762.323134.12619788.766133.09039807.653134.86199830.318 134.966
9837.874134.21259857.863134.57679864.428 133.7219913.665132.94399930.077132.0065
9936.642 130.6889959.619131.38029982.596129.804710008.86129.677510100.76132.0719
10144.28132.100510185.01135.205810251.11 136.98310334.34140.847210380.34141.3557
#Mann= 3 , 0 , 0
9349.353   0.084       09349.353   0.084       010380.34   0.084       0
#XS Ineff= 2 , 0
       09841.439                       0
Bank Sta=9349.353,10380.34
Exp/Cntr=0.3,0.1

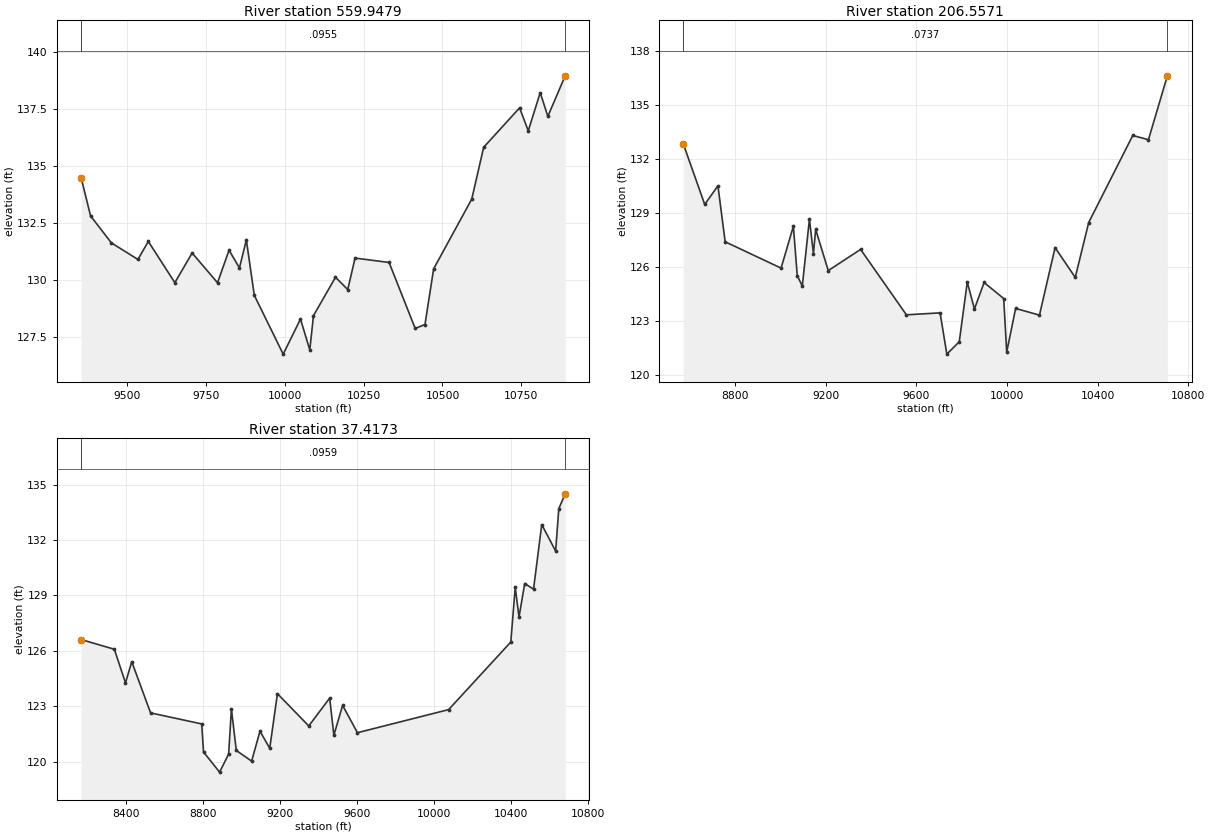
Type RM Length L Ch R = 1 ,559.9479,353.390800,353.390800,353.390800
XS GIS Cut Line= 6
1228001.22563663626086.529800503 1227976.1082651 626067.18653737
1227528.56476828 625847.18842575 1227415.5667491625733.315326303
1227231.80117005625617.5194487271226635.73312572625425.777280658
#Sta/Elev= 30
9354.602134.47869384.593132.80069450.598131.61959534.681130.89279567.583131.6835
9651.666129.87429706.503131.17549786.931129.87029823.489 131.2989856.391130.5195
9878.326131.74689903.521129.31859995.091126.7388 10049.9128.276510079.43 126.923
10091.07128.425810160.87130.112210199.65129.571310222.92130.952610330.74130.7604
10413.46127.865310444.47128.036610472.04130.483510592.67133.537310630.58135.8142
10744.31137.542310771.88136.536510809.79138.210610833.92  137.1710888.92138.9483
#Mann= 3 , 0 , 0
9354.602  0.0955       09354.602  0.0955       010888.92  0.0955       0
#XS Ineff= 2 , 0
       09855.691        10229.65       0
Bank Sta=9354.602,10888.92
Exp/Cntr=0.3,0.1

Type RM Length L Ch R = 1 ,206.5571,169.139800,169.139800,169.139800
XS GIS Cut Line= 6
1228642.82581854626267.429352045 1228392.4600375625948.955324739
1227644.09570587625453.7201327531227543.29544479625435.809511289
1227313.08317605625425.7772806581226814.97036982625379.925892621
#Sta/Elev= 30
8572.399132.86148666.904129.49538725.298130.52688757.149127.4179 9003.84125.9541
9058.117 128.2799075.181125.53769097.458124.95569128.931128.67569146.521126.7622
9156.471128.10739211.916 125.8169354.597126.99329556.727123.35629705.353123.4661
9735.078121.1719 9789.87121.85629825.277125.18029856.751123.68029899.513125.1543
9986.016124.26049999.142 121.28410038.52123.712610143.64 123.33910212.66127.0933
10301.62125.436710360.92128.488510555.31133.3292 10624.5133.092510707.95136.6446
#Mann= 3 , 0 , 0
8572.399  0.0737       08572.399  0.0737       010707.95  0.0737       0
#XS Ineff= 2 , 0
       09786.203        10148.14       0
Bank Sta=8572.399,10707.95
Exp/Cntr=0.3,0.1

Type RM Length L Ch R = 1 , 37.4173,0.000000,0.000000,0.000000
XS GIS Cut Line= 5
1229223.07488385626023.9522932771227853.50852522625380.482224852
1227456.37310854625237.253058195 1227294.6977613625189.510002643
1226881.28630301625168.893683195
#Sta/Elev= 30
8164.997126.61188337.771126.08818395.769124.26748428.393125.41218526.266122.6418
8792.168122.04368801.758120.52338885.131119.43348932.255120.40438946.755122.8575
8972.129120.60599051.877120.02989095.376121.65079146.124 120.7239185.998123.6828
9349.119121.93419457.866123.44179479.616 121.4329525.119123.04729602.271121.5675
10076.55122.818910399.99126.478210422.98129.441710442.69127.830810472.26129.6454
10518.25129.343610560.95132.839610633.22131.403610649.64133.703110682.87134.5041
#Mann= 3 , 0 , 0
8164.997  0.0959       08164.997  0.0959       010682.87  0.0959       0
#XS Ineff= 2 , 0
       09700.049        10118.93       0
Bank Sta=8164.997,10682.87
Exp/Cntr=0.3,0.1